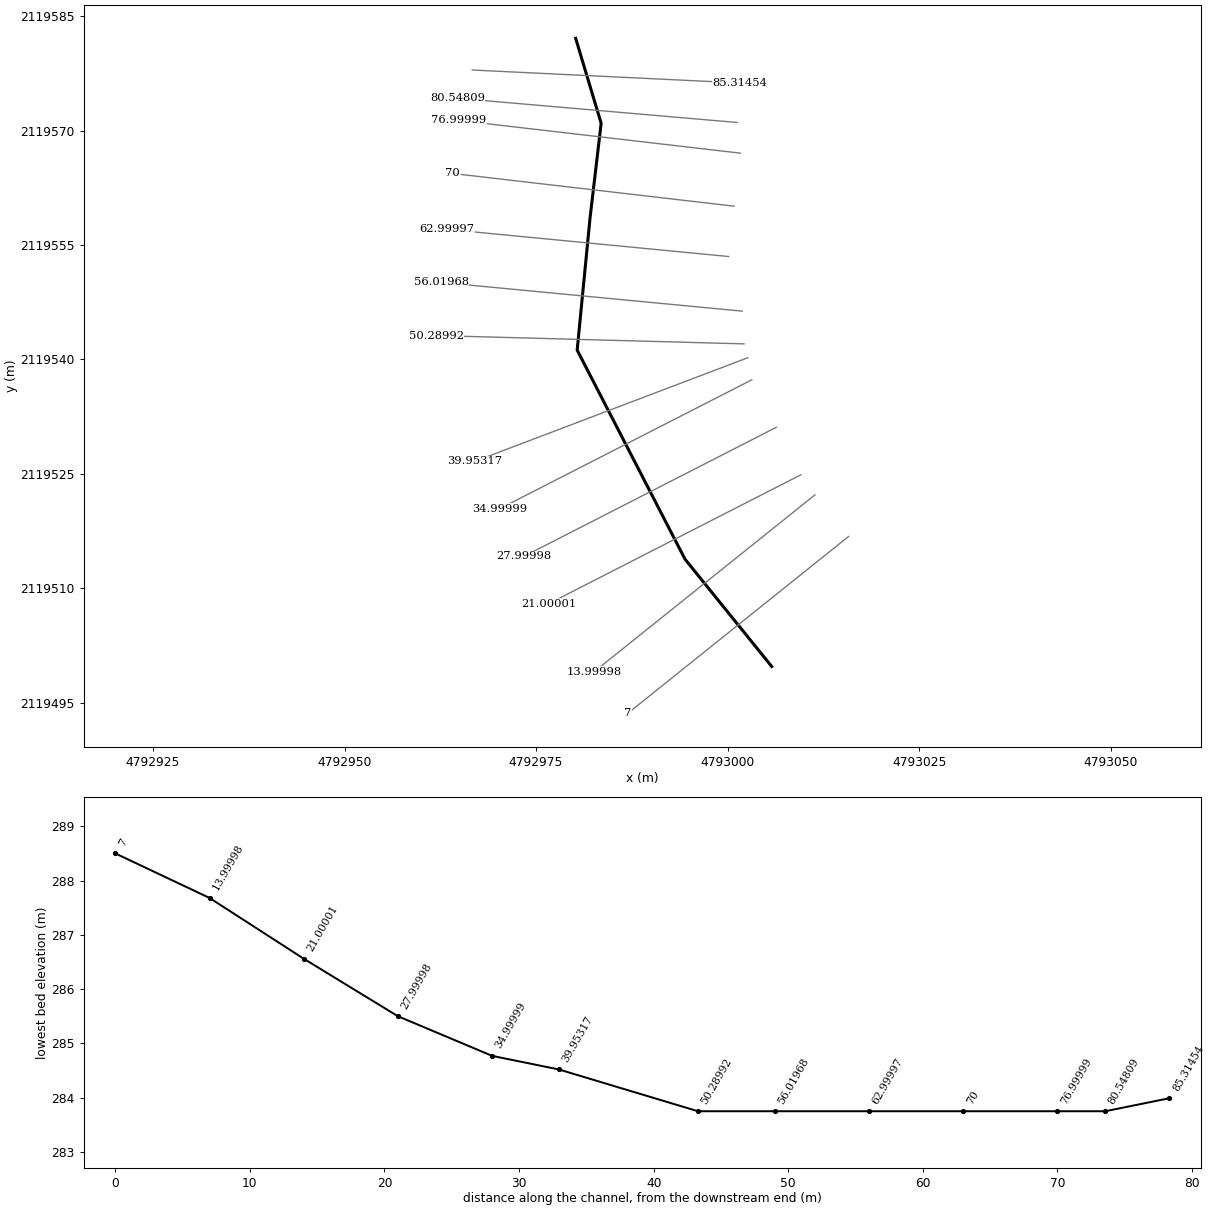
--- Modelo2.prj (project) ---

Proj Title=Modelo2
Current Plan=p02
Default Exp/Contr=0.3,0.1
SI Units
Geom File=g01
Flow File=f01
Plan File=p01
Plan File=p02
Y Axis Title=Elevation
X Axis Title(PF)=Main Channel Distance
X Axis Title(XS)=Station
BEGIN DESCRIPTION:
END DESCRIPTION:
DSS Export Rating Curves= 0
DSS Export Rating Curve Sorted= 0
DSS Export Volume Flow Curves= 0
DXF Filename=Modelo.
DXF OffsetX= 0
DXF OffsetY= 0
DXF ScaleX= 1
DXF ScaleY= 10

--- Modelo2.p02 (plan) ---

Plan Title=Plan 02
Program Version=6.41
Short Identifier=Plan 02
Geom File=g01
Flow File=f01
Supercritical Flow
K Sum by GR= 0
Std Step Tol= 0.003
Critical Tol= 0.003
Num of Std Step Trials= 20
Max Error Tol= 0.1
Flow Tol Ratio= 0.001
Split Flow NTrial= 30
Split Flow Tol= 0.006
Split Flow Ratio= 0.02
Log Output Level= 0
Friction Slope Method= 1
Unsteady Friction Slope Method= 2
Unsteady Bridges Friction Slope Method= 1
Parabolic Critical Depth
Global Vel Dist= 0 , 0 , 0
Global Log Level= 0
CheckData=True
Encroach Param=-1 ,0,0, 0
Flow Ratio Tolerance=0.1
Flow Ratio Min Ratio=0.5
Flow Ratio Max Ratio=4
Flow Ratio Max Iterations= 10
Computation Interval=1MIN
Output Interval=1HOUR
Instantaneous Interval=1HOUR
Mapping Interval=1HOUR
Computation Time Step Use Courant=        0
Computation Time Step Use Time Series=    0
Computation Time Step Count To Double=0
Computation Time Step Max Doubling=0
Computation Time Step Max Halving=0
Computation Time Step Residence Courant=0
Run HTab= 0
Run UNet= 0
Run Sediment= 0
Run PostProcess= 0
Run WQNet= 0
Run RASMapper= 0
UNET Theta= 1
UNET Theta Warmup= 1
UNET ZTol= 0.006
UNET ZSATol= 0.006
UNET MxIter= 20
UNET Max Iter WO Improvement= 0
UNET MaxInSteps= 0
UNET DtIC= 0
UNET DtMin= 0
UNET MaxCRTS= 20
UNET WFStab= 2
UNET SFStab= 1
UNET WFX= 1
UNET SFX= 1
UNET Gravity=9.80665
UNET 1D Methodology=Finite Difference
UNET DSS MLevel= 4
UNET Pardiso=0
UNET DZMax Abort= 30
UNET Use Existing IB Tables=-1
UNET Froude Reduction=False
UNET Froude Limit= 0.8
UNET Froude Power= 4
UNET D1 Cores= 0
UNET WindReference=Eulerian
UNET WindDragFormulation=Hsu (1988)
UNET D2 Coriolis=0
UNET D2 Cores= 0
UNET D2 Theta= 1
UNET D2 Theta Warmup= 1
UNET D2 Z Tol= 0.003
UNET D2 Volume Tol= 0.003
UNET D2 Max Iterations= 20
UNET D2 Equation= 0
UNET D2 RampUpFraction=0.1
UNET D2 TimeSlices= 1
UNET D2 Turbulence Formulation=None
UNET D2 Eddy Viscosity=0.3
UNET D2 Transverse Eddy Viscosity=0.1
UNET D2 Smagorinsky Mixing=0.05
UNET D2 BCVolumeCheck=0
UNET D2 Cores=0
UNET D2 SolverType=PARDISO (Direct)
UNET D2 Minimum Iterations= 3
UNET D2 Maximum Iterations= 30
UNET D2 Restart Number= 10
UNET D2 Relaxation Coeff=1.3
UNET D2 SOR Precondition Iterations= 10
UNET D2 ILUT Maximum Fill= 8
UNET D2 ILUT Tolerance=1E-08
UNET D2 Convergence Tolerance=0.00001
UNET D1D2 MaxIter= 0
UNET D1D2 ZTol=0.003
UNET D1D2 QTol=0.1
UNET D1D2 MinQTol=0.03
Write IC File= 0
Write IC File at Fixed DateTime=0
Write IC File at Sim End=0
Echo Input=False
Echo Parameters=False
Echo Output=False
Write Detailed= 0
HDF Write Warmup=0
HDF Write Time Slices=0
HDF Flush=0
HDF Compression= 1
HDF Chunk Size= 1
HDF Spatial Parts= 1
HDF Use Max Rows=0
HDF Fixed Rows= 1
Calibration Method= 0
Calibration Iterations= 20
Calibration Max Change=0.05
Calibration Tolerance=0.2
Calibration Maximum=1.5
Calibration Minimum=0.5
Calibration Optimization Method= 1
WQ AD Non Conservative
WQ ULTIMATE=-1
WQ Max Comp Step=1HOUR
WQ Output Interval=15MIN
WQ Output Selected Increments= 0
WQ Create Restart=0
WQ Fixed Restart=0
WQ System Summary=0
WQ Write To DSS=0
Sorting and Armoring Iterations= 10
XS Update Threshold= 0.02
Bed Roughness Predictor= 0
Hydraulics Update Threshold= 0.02
Energy Slope Method= 1
Volume Change Method= 1
Sediment Retention Method= 0
Sediment TS Multiplier= 1
Warm Up Method= 0
XS Weighting Method= 0
Number of US Weighted Cross Sections= 1
Number of DS Weighted Cross Sections= 1
Upstream XS Weight=0
Main XS Weight=1
Downstream XS Weight=0
Number of DS XS's Weighted with US Boundary= 1
Upstream Boundary Weight= 1
Weight of XSs Associated with US Boundary= 0
Number of US XS's Weighted with DS Boundary= 1
Downstream Boundary Weight= 0.5
Weight of XSs Associated with DS Boundary= 0.5
Percentile Method= 0
Sediment Output Level= 3
Mass or Volume Output= 0
Output Increment Type= 1
Profile and TS Output Increment= 1
Transport Output Increment 1
XS Output Flag= 0
XS Output Increment= 10
Read HDF5 Sediment Hotstart= 0
Sediment Hotstart Type= 0
Write Gradation File= 0
Read Gradation Hotstart= 0
Write HDF5 File= 1
Write Binary Output= 1
Write DSS Sediment File= 0
DSS Sediment Output Type= 1
SV Curve= 0
Specific Gage Flag= 0
Subcell Erosion Methods= 0
Subcell Deposition Methods= 0
Advection Scheme= 1
Matrix Solver= 0
Implicit Weighting Factor= 1
Maximum Outer Loop Convergence Iterations= 5
Convergence Maximum Absolute= 0.001
Convergence RMSE= 0.0001
Grain Fractions Max Abs Error= 0.001
Max Subgrid Regions= 1
Max Subgrid Length Scale= 3.402823E+38
Initial Layer Thickness= 3
Min Layer Thickness= 0.1
Max Layer Thickness= 6
Number of Layers= 5

--- Modelo2.p01 (plan) ---

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Plan Title=Plan 01
Short Identifier=Plan 01
Geom File=g01
Flow File=f01
Mixed Flow

--- Modelo2.f01 (steady flow) ---

Flow Title=Flowd
Program Version=6.41
Number of Profiles= 6
Profile Names=TR2,TR5,TR10,TR25,TR50,TR100
River Rch & RM=Quebrada 1,1               ,85.31454
     1.6    1.88    2.14    2.52    2.85    3.23
Boundary for River Rch & Prof#=Quebrada 1,1               , 1
Up Type= 3
Up Slope=0.002
Dn Type= 3
Dn Slope=0.002
Boundary for River Rch & Prof#=Quebrada 1,1               , 2
Up Type= 3
Up Slope=0.002
Dn Type= 3
Dn Slope=0.002
Boundary for River Rch & Prof#=Quebrada 1,1               , 3
Up Type= 3
Up Slope=0.002
Dn Type= 3
Dn Slope=0.002
Boundary for River Rch & Prof#=Quebrada 1,1               , 4
Up Type= 3
Up Slope=0.002
Dn Type= 3
Dn Slope=0.002
Boundary for River Rch & Prof#=Quebrada 1,1               , 5
Up Type= 3
Up Slope=0.002
Dn Type= 3
Dn Slope=0.002
Boundary for River Rch & Prof#=Quebrada 1,1               , 6
Up Type= 3
Up Slope=0.002
Dn Type= 3
Dn Slope=0.002
DSS Import GetInterval= 0
DSS Import GetPeak= 0
DSS Import FillOption= 0

--- Modelo2.g01 (geometry) ---

Geom Title=geometry
Program Version=6.41

River Reach=Quebrada 1      ,1
Reach XY= 30
     4792980.172     2119582.089    4792983.4971    2119570.9502
    4792982.0401    2119558.4663     4792980.367    2119541.2131
    4792981.0301    2119539.9217    4792981.7464     2119538.527
    4792982.4067     2119537.241    4792982.4683    2119537.1212
    4792983.0039     2119536.078     4792983.213     2119535.671
    4792983.9777    2119534.1817    4792984.2288    2119533.6929
    4792984.3176    2119533.5198    4792985.7626     2119530.706
    4792987.3241     2119527.665    4792988.1702    2119526.0175
    4792989.1989    2119524.0141    4792989.3082    2119523.8014
    4792989.4106    2119523.6018    4792993.1491    2119516.3218
    4792993.2307    2119516.1627    4792994.4429    2119513.8022
     4792996.723    2119510.9681    4792996.8804    2119510.7723
    4792997.0573    2119510.5526    4792998.0476    2119509.3215
     4792999.489      2119507.53    4792999.7272    2119507.2338
    4793002.2311    2119504.1216    4793005.7671    2119499.7263

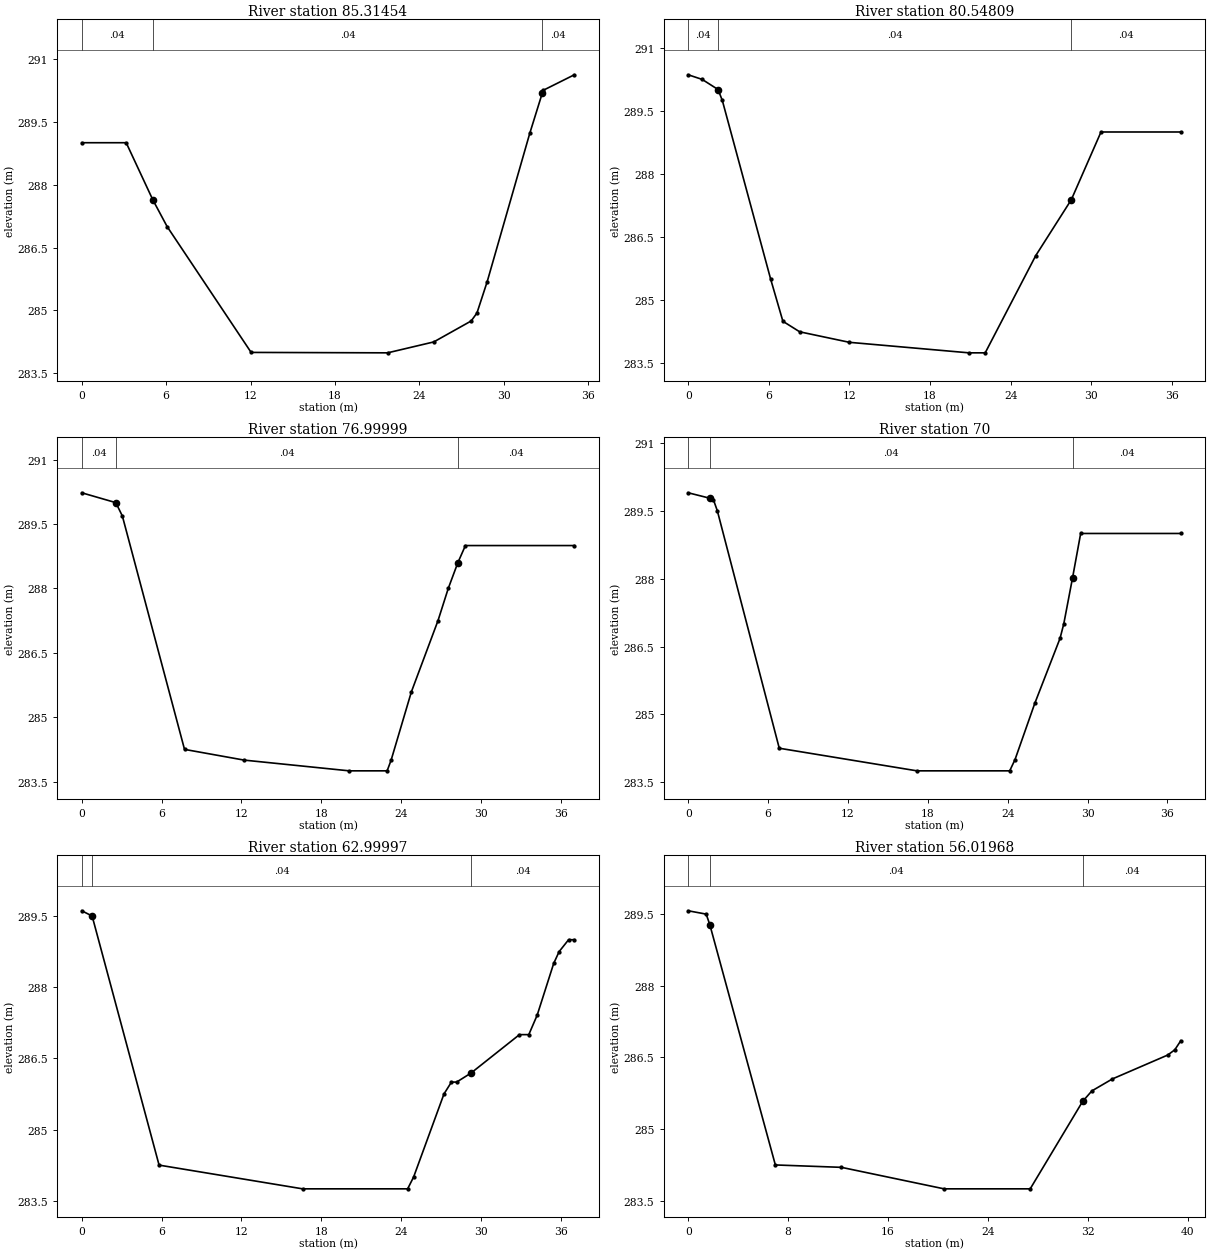
Type RM Length L Ch R = 1 ,85.31454,9.19,4.77,4.2
XS GIS Cut Line= 2
    4792966.6735    2119577.9351    4793001.6449    2119576.2386
#Sta/Elev= 14
       0     289    3.16     289    5.05  287.64    6.07     287   12.04     284
   21.74  283.99   25.02  284.25   27.68  284.75   28.09  284.94   28.82  285.69
   31.84  289.22   32.73  290.18    32.8  290.25   35.01  290.62
#Mann= 3 ,0,0
       0     .04       0    5.05     .04       0   32.73     .04       0
Bank Sta=5.05,32.73
XS Rating Curve= 0 ,0
Exp/Cntr=0.3,0.1

Type RM Length L Ch R = 1 ,80.54809,6,3.55,3.24
XS GIS Cut Line= 2
    4793001.2561    2119571.0547    4792964.7278    2119574.2299
#Sta/Elev= 14
       0  290.36    1.04  290.25    2.22  290.01    2.54  289.75    6.14   285.5
    7.05   284.5     8.3  284.25      12     284    20.9  283.75   22.11  283.75
   25.87  286.06   28.52  287.39   30.73     289   36.67     289
#Mann= 3 ,0,0
       0     .04       0    2.22     .04       0   28.52     .04       0
Bank Sta=2.22,28.52
XS Rating Curve= 0 ,0
Exp/Cntr=0.3,0.1

Type RM Length L Ch R = 1 ,76.99999,20.87,7,7.06
XS GIS Cut Line= 2
    4793001.6658    2119567.0354    4792964.9152    2119571.3246
#Sta/Elev= 14
       0  290.23    2.56     290    3.05  289.69    7.72  284.25    12.2     284
   20.09  283.75   22.94  283.75   23.24     284   24.76  285.59   26.76  287.25
   27.53     288   28.25   288.6   28.82     289      37     289
#Mann= 3 ,0,0
       0     .04       0    2.56     .04       0   28.25     .04       0
Bank Sta=2.56,28.25
XS Rating Curve= 0 ,0
Exp/Cntr=0.3,0.1

Type RM Length L Ch R = 1 ,70      ,6,7,7.27
XS GIS Cut Line= 2
    4793000.8543    2119560.0826    4792964.1038    2119564.3718
#Sta/Elev= 14
       0   289.9    1.62  289.78    1.89  289.75    2.19   289.5    6.84  284.25
   17.18  283.75   24.15  283.75   24.55     284   26.03  285.24   27.93  286.68
   28.21     287   28.87  288.02   29.48     289      37     289
#Mann= 3 ,0,0
       0     .04       0    1.62     .04       0   28.87     .04       0
Bank Sta=1.62,28.87
XS Rating Curve= 0 ,0
Exp/Cntr=0.3,0.1

Type RM Length L Ch R = 1 ,62.99997,6,6.98,7
XS GIS Cut Line= 2
    4793000.1435    2119553.4821    4792963.3163    2119557.0534
#Sta/Elev= 17
       0  289.61     .78   289.5    5.81  284.25   16.59  283.75   24.48  283.75
   24.93     284   27.21  285.75   27.77     286   28.16     286   29.24  286.19
   32.88     287   33.58     287   34.21  287.41   35.45   288.5   35.86  288.75
   36.57     289      37     289
#Mann= 3 ,0,0
       0     .04       0     .78     .04       0   29.24     .04       0
Bank Sta=0.78,29.24
XS Rating Curve= 0 ,0
Exp/Cntr=0.3,0.1

Type RM Length L Ch R = 1 ,56.01968,15.96,5.73,6.56
XS GIS Cut Line= 2
    4793001.9136    2119546.3199    4792962.6407     2119550.086
#Sta/Elev= 13
       0  289.57    1.44   289.5    1.73  289.28    6.98  284.25   12.27   284.2
   20.49  283.75   27.39  283.75   31.59  285.58   32.33   285.8   33.97  286.05
    38.4  286.55   38.97  286.66   39.45  286.85
#Mann= 3 ,0,0
       0     .04       0    1.73     .04       0   31.59     .04       0
Bank Sta=1.73,31.59
XS Rating Curve= 0 ,0
Exp/Cntr=0.3,0.1

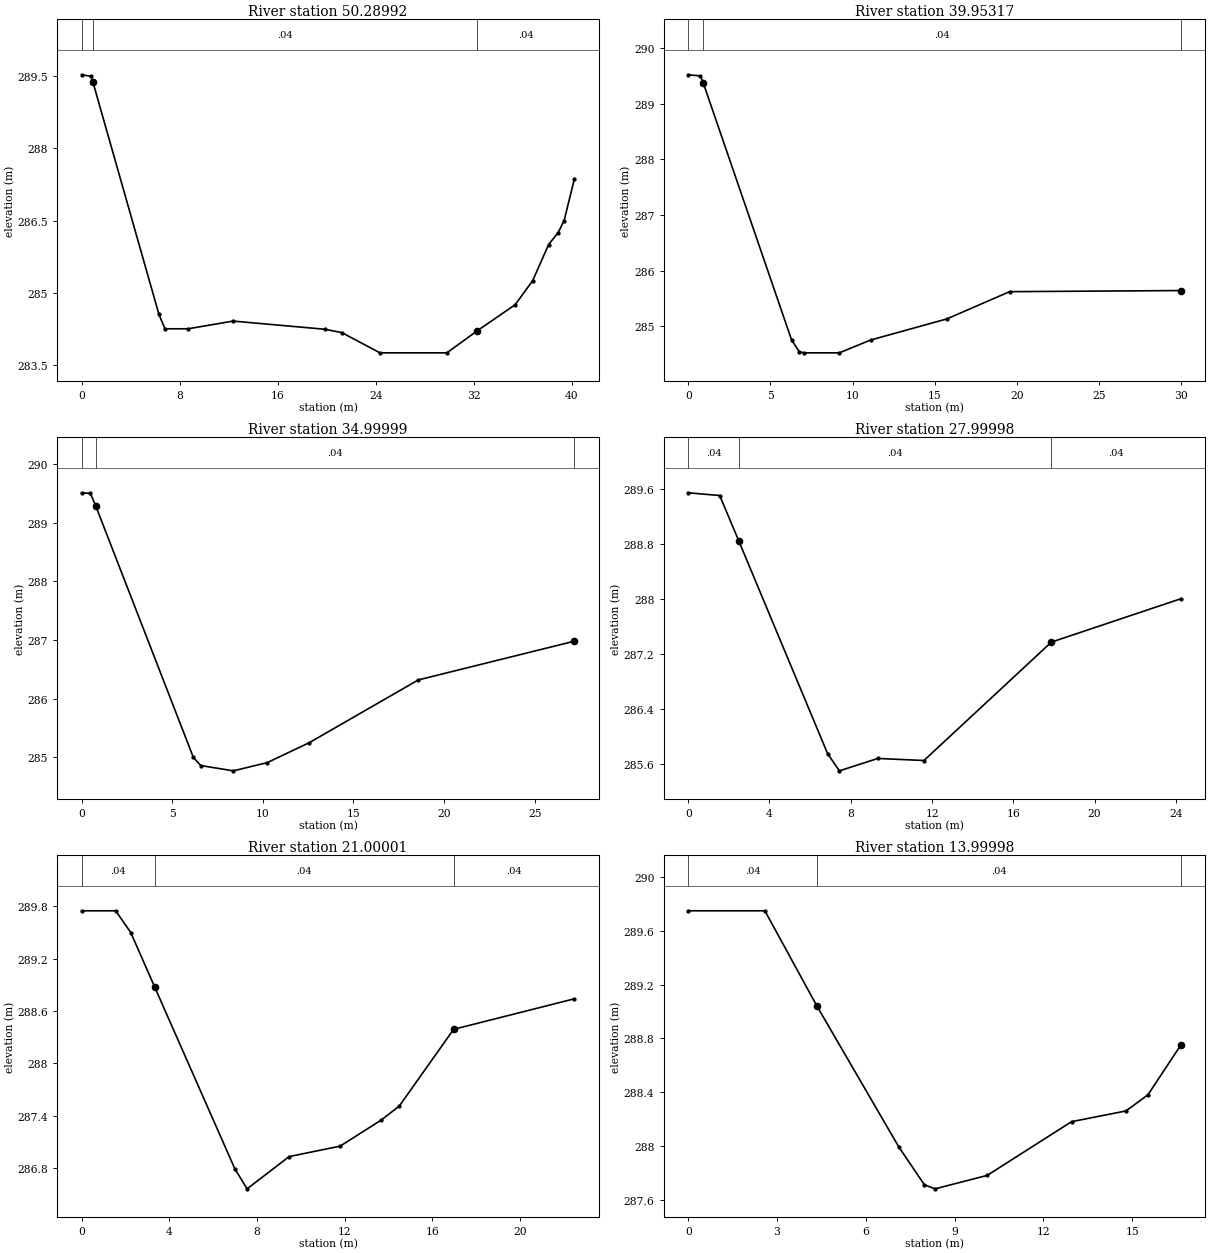
Type RM Length L Ch R = 1 ,50.28992,6,10.34,15
XS GIS Cut Line= 2
    4793002.1542    2119542.0311     4792961.965    2119543.1187
#Sta/Elev= 18
       0  289.53     .74   289.5      .9  289.39     6.3  284.55    6.79  284.25
    8.68  284.25   12.35  284.41   19.85  284.24   21.23  284.17   24.34  283.75
    29.8  283.75   32.23   284.2   35.37  284.75    36.8  285.25    38.1     286
   38.88  286.25   39.37   286.5    40.2  287.36
#Mann= 3 ,0,0
       0     .04       0      .9     .04       0   32.23     .04       0
Bank Sta=0.9,32.23
XS Rating Curve= 0 ,0
Exp/Cntr=0.3,0.1

Type RM Length L Ch R = 1 ,39.95317,6,4.95,6.35
XS GIS Cut Line= 2
    4793002.6304    2119540.2054    4792967.0526    2119526.6425
#Sta/Elev= 11
       0  289.52     .74   289.5     .92  289.37    6.29  284.75    6.76  284.54
    7.05  284.52    9.19  284.52   11.09  284.75   15.73  285.13   19.55  285.62
   29.96  285.64
#Mann= 3 ,0,0
       0     .04       0     .92     .04       0   29.96     .04       0
Bank Sta=0.92,29.96
XS Rating Curve= 0 ,0
Exp/Cntr=0.3,0.1

Type RM Length L Ch R = 1 ,34.99999,6,7,7.03
XS GIS Cut Line= 2
    4793003.1642    2119537.3173    4792970.2502    2119520.4155
#Sta/Elev= 10
       0  289.51     .48   289.5     .78  289.28    6.16     285    6.57  284.86
    8.37  284.77   10.24  284.91   12.56  285.25   18.58  286.32   27.19  286.98
#Mann= 3 ,0,0
       0     .04       0     .78     .04       0   27.19     .04       0
Bank Sta=0.78,27.19
XS Rating Curve= 0 ,0
Exp/Cntr=0.3,0.1

Type RM Length L Ch R = 1 ,27.99998,7.06,7,7.04
XS GIS Cut Line= 2
    4793006.3618    2119531.0904    4792973.4479    2119514.1885
#Sta/Elev= 9
       0  289.54    1.55   289.5    2.49  288.84    6.86  285.75    7.44   285.5
    9.33  285.68    11.6  285.65   17.87  287.37   24.24     288
#Mann= 3 ,0,0
       0     .04       0    2.49     .04       0   17.87     .04       0
Bank Sta=2.49,17.87
XS Rating Curve= 0 ,0
Exp/Cntr=0.3,0.1

Type RM Length L Ch R = 1 ,21.00001,3.63,7,9.43
XS GIS Cut Line= 2
    4793009.5595    2119524.8634    4792976.6455    2119507.9616
#Sta/Elev= 12
       0  289.75    1.55  289.75    2.24   289.5    3.34  288.87    6.99  286.79
    7.55  286.56    9.47  286.93    11.8  287.05   13.68  287.35    14.5  287.51
   16.98  288.39   22.49  288.74
#Mann= 3 ,0,0
       0     .04       0    3.34     .04       0   16.98     .04       0
Bank Sta=3.34,16.98
XS Rating Curve= 0 ,0
Exp/Cntr=0.3,0.1

Type RM Length L Ch R = 1 ,13.99998,7.31,7,7
XS GIS Cut Line= 2
    4793011.4057    2119522.2309    4792982.5771     2119499.038
#Sta/Elev= 11
       0  289.75    2.59  289.75    4.35  289.04    7.12  287.99    7.98  287.71
    8.34  287.68    10.1  287.78   12.95  288.18   14.79  288.26   15.53  288.38
   16.64  288.75
#Mann= 3 ,0,0
       0     .04       0    4.35     .04       0   16.64     .04       0
Bank Sta=4.35,16.64
XS Rating Curve= 0 ,0
Exp/Cntr=0.3,0.1

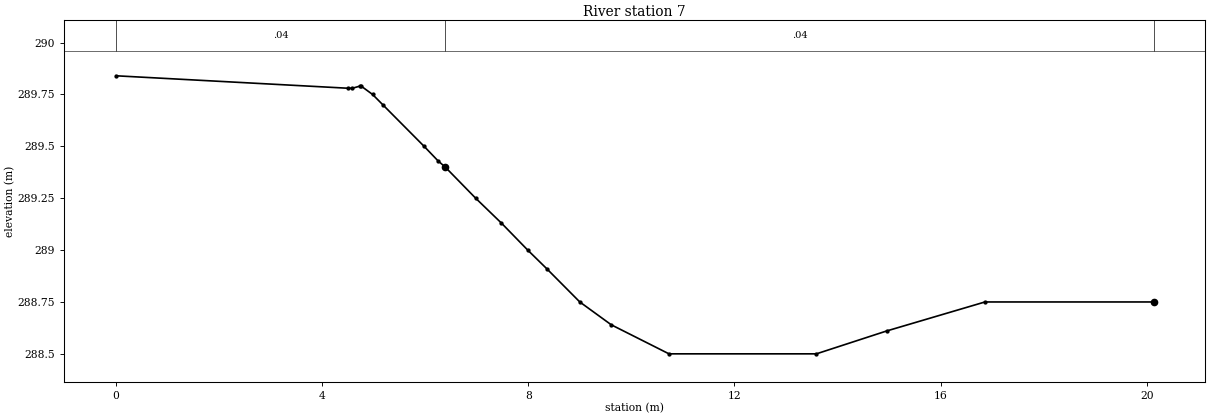
Type RM Length L Ch R = 1 ,7       ,9.15,7,4.75
XS GIS Cut Line= 2
    4793015.7936    2119516.7768    4792986.9649    2119493.5839
#Sta/Elev= 21
       0  289.84     4.5  289.78    4.59  289.78    4.73  289.79    4.76  289.79
    4.98  289.75    5.18   289.7    5.98   289.5    6.25  289.43    6.39   289.4
    6.98  289.25    7.48  289.13    7.99     289    8.36  288.91       9  288.75
    9.61  288.64   10.73   288.5   13.59   288.5   14.95  288.61   16.86  288.75
   20.13  288.75
#Mann= 3 ,0,0
       0     .04       0    6.39     .04       0   20.13     .04       0
Bank Sta=6.39,20.13
XS Rating Curve= 0 ,0
Exp/Cntr=0.3,0.1
LCMann Table=0

Chan Stop Cuts=-1
Use User Specified Reach Order=0
Composite Channel Slope=5